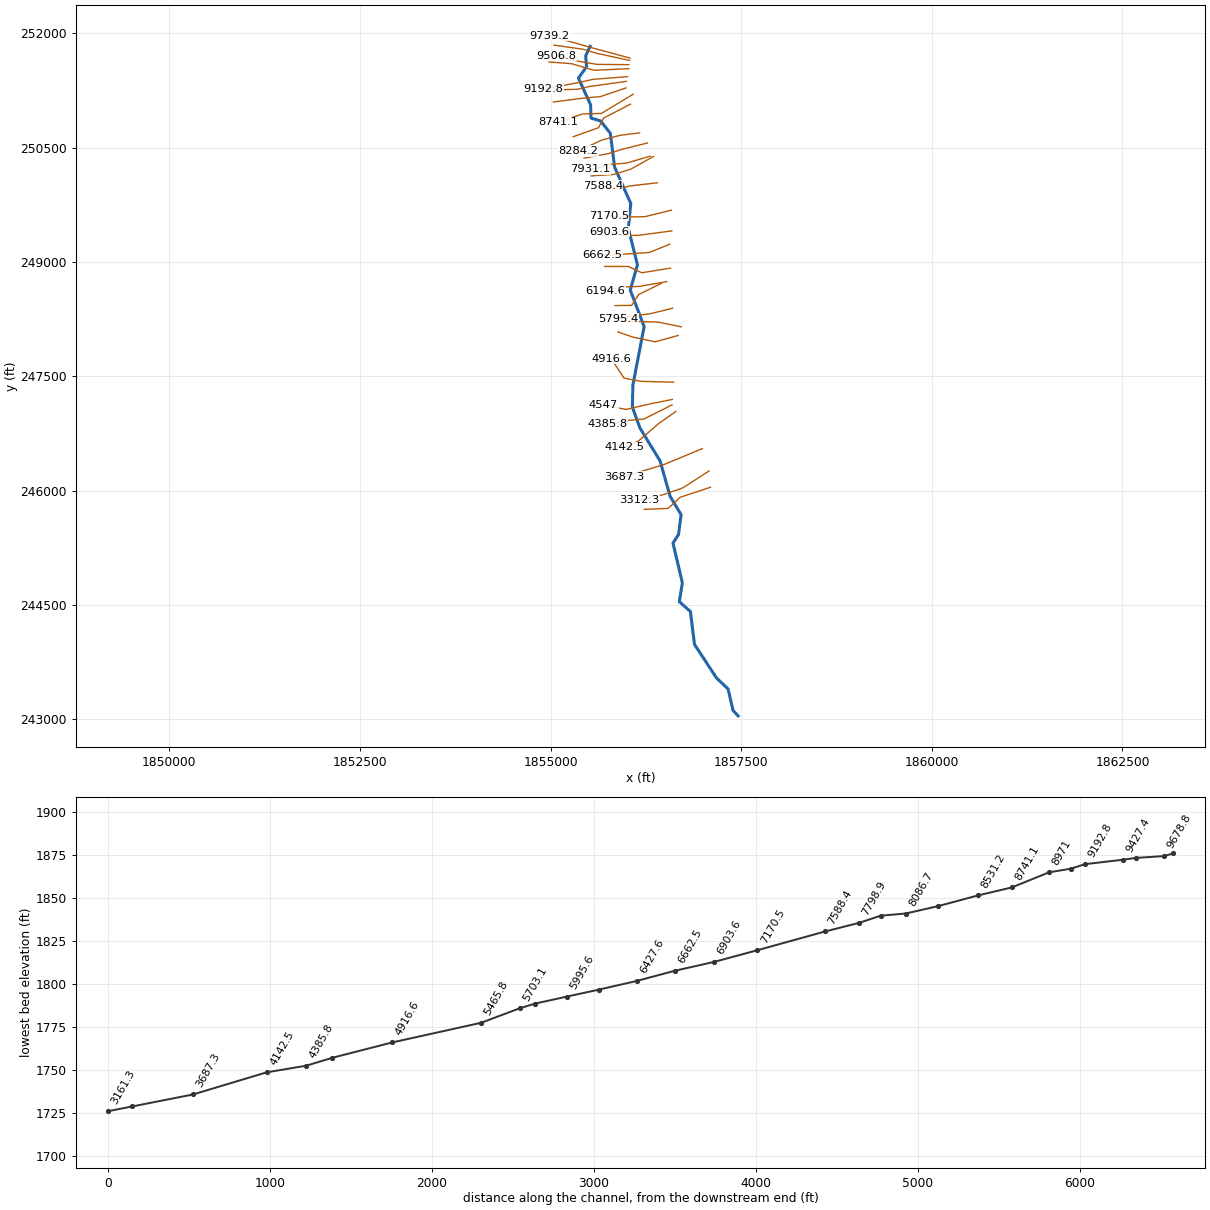
--- OldSlabFk.prj (project) ---

Proj Title=OldSlabFk
Current Plan=p01
Default Exp/Contr=0,0
English Units
Geom File=g01
Flow File=f01
Plan File=p01
BEGIN DESCRIPTION:
END DESCRIPTION:
DSS Export Rating Curves= 0
DSS Export Rating Curve Sorted= 0
DSS Export Volume Flow Curves= 0
DXF OffsetX= 0
DXF OffsetY= 0
DXF ScaleX= 0
DXF ScaleY= 0

--- OldSlabFk.p01 (plan) ---

Plan Title=Floodplain
Program Version=4.00
Geom File=g01
Flow File=f01
K Sum by GR=0
Std Step Tol=0.01
Critical Tol=0.01
Num of Std Step Trials=20
Max Error Tol=0.3
Flow Tol Ratio=0.001
Split Flow NTrial=30
Split Flow Tol=0.02
Split Flow Ratio=0.02
Log Output Level=0
Friction Slope Method=1
Unsteady Friction Slope Method=2
Unsteady Bridges Friction Slope Method=1
Global Log Level=0
CheckData=False
Run HTab=0
Run UNet=0
Run PostProcess=0
UNET Theta=0
UNET Theta Warmup=0
UNET ZTol=0
UNET ZSATol=0
UNET MxIter=0
UNET MaxInSteps=0
UNET DtIC=0
UNET DtMin=0
UNET MaxCRTS=0
UNET WFStab=0
UNET SFStab=0
UNET WFX=0
UNET SFX=0
UNET DSS MLevel=0
UNET DZMax Abort=0
UNET Convert EG Bridges=0
UNET Use Existing IB Tables=0
UNET Froude Limit=0
UNET Froude Power=0
Write IC File=0
Echo Input=False
Echo Output=False
Write Detailed=0

--- OldSlabFk.f01 (steady flow) ---

Flow Title=NFF Regression Equation
Program Version=4.00
Number of Profiles=1
Profile Names=P100yr
River Rch & RM=OldSlabFk,Main      ,9739.2
503.8450
River Rch & RM=OldSlabFk,Main      ,9427.4
601.4168
River Rch & RM=OldSlabFk,Main      ,9106.9
788.9455
River Rch & RM=OldSlabFk,Main      ,7588.4
813.1237
River Rch & RM=OldSlabFk,Main      ,4916.6
880.4852
River Rch & RM=OldSlabFk,Main      ,4547
977.7583
River Rch & RM=OldSlabFk,Main      ,2712.9
1027.781
Boundary for River Rch & Prof#=OldSlabFk,Main      ,1
Up Type=0
Dn Type=3
Dn Slope=0.015467

--- OldSlabFk.g01 (geometry) ---

Geom Title=USGS 10m DEM
Program Version=4.00

River Reach=OldSlabFk       ,Main
Reach XY= 30
     1855518.039      251826.462     1855460.534      251705.943
     1855471.219       251558.29     1855365.337       251412.58
     1855525.618      251060.934     1855529.503      250888.025
     1855656.756      250849.169     1855784.009      250687.917
     1855840.351      250243.017     1856052.115      249767.032
     1856020.059      249441.614     1856139.392      248963.156
     1856044.928      248630.838     1856227.453      248153.055
       1856079.8      247386.298     1856073.324      247094.879
     1856171.759      246824.182     1856435.979      246391.586
      1856568.09      245926.611     1856711.856      245686.999
     1856678.181       245425.37      1856605.65      245313.983
     1856728.694      244792.018     1856688.543      244544.635
     1856833.605      244416.411     1856888.003      243983.815
     1857176.459      243544.522     1857328.017      243399.928
     1857392.346      243119.713      1857459.97      243047.113

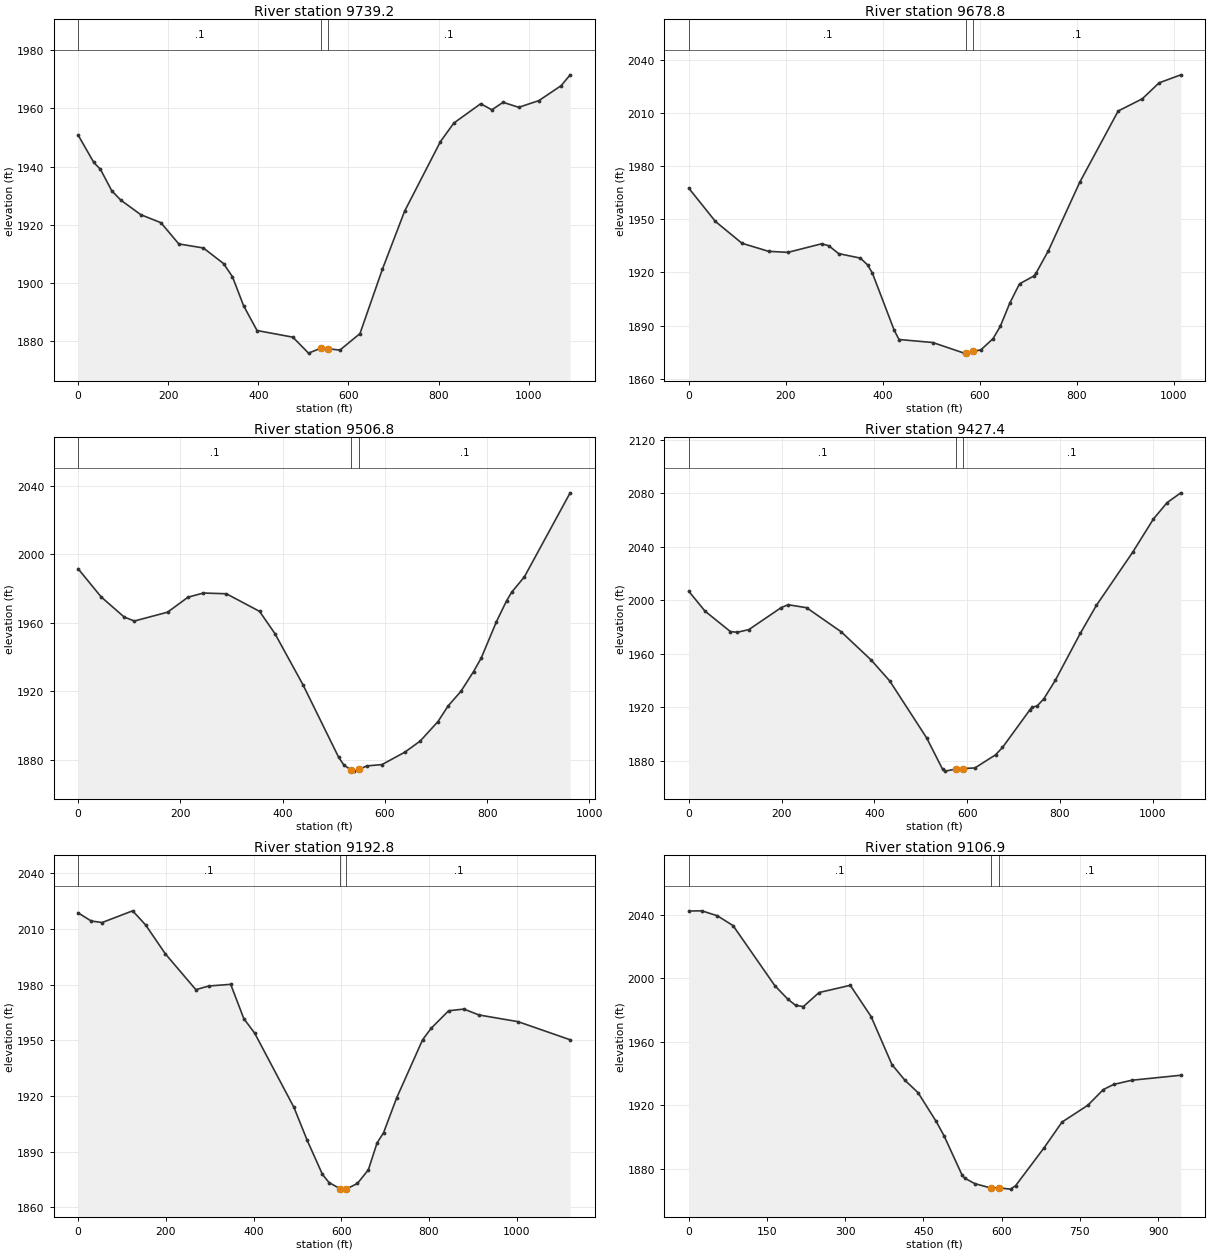
Type RM Length L Ch R = 1 ,9739.2  ,61.2,60.4,56.9
XS GIS Cut Line= 3
     1856042.401       251674.21     1855515.305      251816.843
     1854990.119      251966.124
#Sta/Elev= 30
       0 1950.84    34.8 1941.43    49.6 1939.07    74.5 1931.75    94.3 1928.57
     139 1923.52   183.7 1920.77   223.4 1913.48     278 1912.09   322.7 1906.75
   342.5 1902.23   367.3 1892.25   397.1 1883.76   476.6 1881.48   511.3    1876
   538.7 1877.69   553.7 1877.54   580.8 1877.03   625.5  1882.7   675.1 1904.71
   724.7 1924.75   804.2 1948.62   833.9 1954.97   893.5  1961.6   918.3 1959.51
   943.1 1962.09   977.9 1960.37  1022.6 1962.67  1072.2 1967.82    1092 1971.52
#Mann= 3 , 0 , 0
       0      .1       0   538.7    .045       0   553.7      .1       0
Bank Sta=538.7,553.7
XS Rating Curve= 0 ,0
Exp/Cntr=0.3,0.1

Type RM Length L Ch R = 1 ,9678.8  ,169.7,172,174.2
XS GIS Cut Line= 4
      1856036.84      251643.027     1855608.644      251735.969
     1855422.761      251790.738     1855044.355      251843.847
#Sta/Elev= 30
       0 1967.63    54.8 1948.85   109.5 1936.53   164.3 1931.96   204.2 1931.38
   273.8 1936.23   288.8 1935.07   308.7 1930.68   353.5 1928.13   368.5  1924.3
   378.4 1919.64   423.2 1887.47   433.2 1882.14   502.8 1880.44   567.4 1874.44
   571.5 1874.62   586.5 1875.39   602.1 1876.32     627 1882.61   641.9 1889.54
   661.7 1902.77   681.6 1913.59   711.4 1918.05   716.3 1919.96   741.1 1932.29
   805.6 1970.89     885 2011.26   934.7 2018.14   969.4 2027.17  1014.1 2031.69
#Mann= 3 , 0 , 0
       0      .1       0   571.5    .045       0   586.5      .1       0
Bank Sta=571.5,586.5
XS Rating Curve= 0 ,0
Exp/Cntr=0.3,0.1

Type RM Length L Ch R = 1 ,9506.8  ,74.2,79.4,77.9
XS GIS Cut Line= 4
     1856025.222      251588.258     1855610.304      251591.577
     1855364.672      251633.069     1855075.889      251707.754
#Sta/Elev= 30
       0  1991.5      45 1975.09      90 1963.35     110 1961.01     175 1966.18
     215 1974.94     245 1977.35     290 1976.92   354.9 1966.64   384.9 1953.65
   439.8 1923.78   509.6 1881.42   519.6 1877.01   534.6 1873.84   539.5 1873.37
   549.6 1874.44   564.4 1876.41   594.3  1877.2   639.1 1884.46     669 1890.93
   703.8 1902.31   723.7 1911.46   748.6 1919.93   773.4  1931.5   788.3 1939.35
   818.2 1960.67     838 1972.82     848 1977.85   872.8 1986.79   962.3 2035.85
#Mann= 3 , 0 , 0
       0      .1       0   534.6    .045       0   549.6      .1       0
Bank Sta=534.6,549.6
XS Rating Curve= 0 ,0
Exp/Cntr=0.3,0.1

Type RM Length L Ch R = 1 ,9427.4  ,231.3,234.6,238.4
XS GIS Cut Line= 4
     1856026.872      251535.534      1855574.37      251513.727
     1855274.519      251600.956      1854980.12      251622.764
#Sta/Elev= 30
       0 2006.72    34.8 1991.94    89.6 1976.62   104.5  1976.1   129.4  1978.1
   199.1 1994.53   214.1 1996.69   253.9 1994.45   328.6 1976.41   393.3 1955.27
   433.1 1939.71   512.5 1897.24   547.2 1873.63   552.2 1872.33   575.4 1873.84
   590.4 1874.29   616.6 1874.69   661.2 1884.54   676.1 1890.01   735.6 1918.33
   740.5 1920.23   750.4  1920.9   765.3 1926.41   789.9 1940.17     844  1975.4
   878.5 1996.18   957.2 2036.17  1001.5 2060.79    1031 2073.01  1060.5 2080.31
#Mann= 3 , 0 , 0
       0      .1       0   575.4    .045       0   590.4      .1       0
Bank Sta=575.4,590.4
XS Rating Curve= 0 ,0
Exp/Cntr=0.3,0.1

Type RM Length L Ch R = 1 ,9192.8  ,86.1,85.9,88.7
XS GIS Cut Line= 4
     1856009.812      251430.847     1855558.854      251395.736
     1855344.561      251348.614     1854901.822      251267.131
#Sta/Elev= 30
       0 2018.71    29.8 2014.32    54.7  2013.5   124.3 2019.81   154.1 2012.13
   198.8 1996.64   268.4  1977.3   298.2 1979.28   347.9 1980.16   377.8 1961.68
   402.6 1953.82   492.2 1913.76   522.1 1896.16     557 1877.71     572 1873.27
   596.8 1870.02   606.9 1869.72   611.8 1869.82   636.8 1872.77   661.8 1880.14
   681.6 1894.63   696.5 1900.16   726.2 1918.87   785.5 1950.29   805.3 1956.55
   844.9 1965.92   879.5 1966.82   914.1 1963.64  1003.2 1960.03  1121.9 1950.27
#Mann= 3 , 0 , 0
       0      .1       0   596.8    .045       0   611.8      .1       0
Bank Sta=596.8,611.8
XS Rating Curve= 0 ,0
Exp/Cntr=0.3,0.1

Type RM Length L Ch R = 1 ,9106.9  ,139.4,135.8,132.3
XS GIS Cut Line= 4
     1855995.348      251369.181     1855495.786      251299.475
     1855353.055      251264.622     1855060.952      251257.983
#Sta/Elev= 30
       0 2042.31      25 2042.43    54.9  2039.3    84.9 2033.11   164.8 1995.35
   189.8 1986.81   204.8 1982.88   219.7 1982.13   249.7 1990.96   309.6 1995.51
   349.6  1975.8   389.5  1945.6   414.5 1935.67   439.5 1927.92   474.4 1909.77
   489.4 1900.76     524    1876   528.9 1874.06   548.5 1870.56   578.9 1867.88
   593.9 1867.92     617 1867.12   626.8 1869.34     681 1893.03   715.7 1909.36
   765.2 1919.95   794.9 1929.85   814.8 1933.08   849.4 1935.71   943.5 1938.85
#Mann= 3 , 0 , 0
       0      .1       0   578.9    .045       0   593.9      .1       0
Bank Sta=578.9,593.9
XS Rating Curve= 0 ,0
Exp/Cntr=0.3,0.1

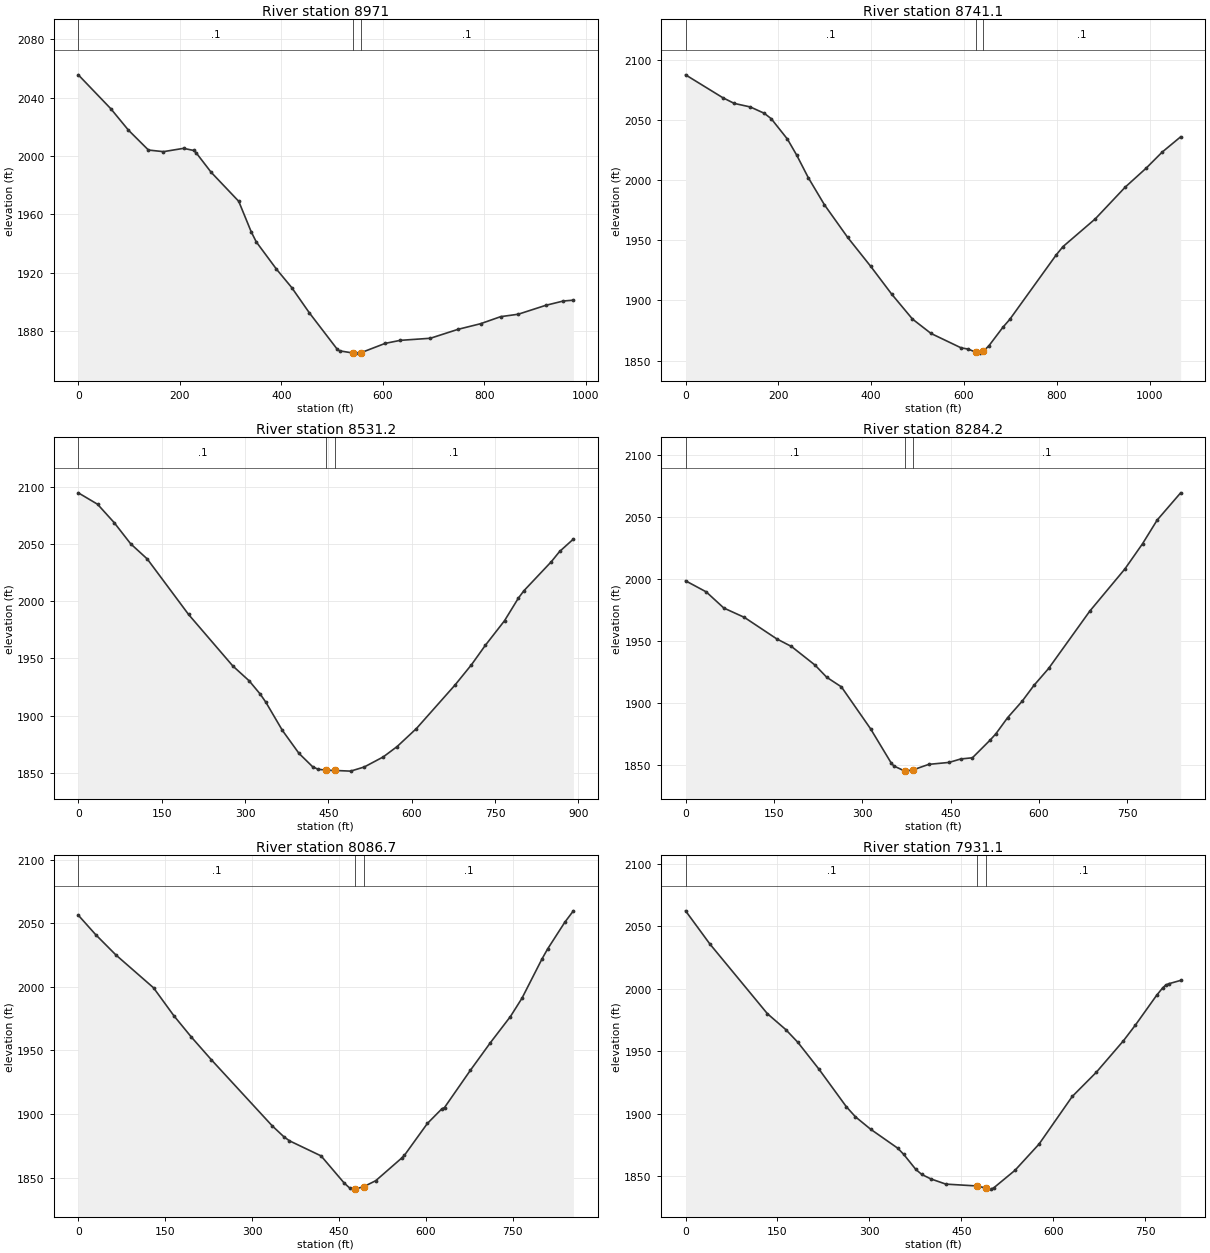
Type RM Length L Ch R = 1 ,8971    ,232.1,230,227.8
XS GIS Cut Line= 4
     1855988.978      251282.714     1855652.347      251168.602
     1855438.601      251149.792     1855036.741      251098.076
#Sta/Elev= 30
       0  2055.6    64.2 2032.32    98.7 2017.73   138.2 2004.07   167.8 2002.98
   207.3 2005.24   227.1 2003.81     232 2002.27   261.6 1988.88     316 1968.97
   340.6 1948.08   350.5  1941.2   390.4 1922.46   420.3 1909.92   455.2 1892.53
   510.1  1867.6   515.1  1866.5   540.9 1865.07   550.1 1864.97   555.9 1865.14
   604.6 1871.66   634.2 1873.72   693.6 1875.16   747.9 1881.26   792.4 1885.12
   831.9 1889.95   866.5 1891.61   920.8 1897.71   955.4 1900.67   975.2 1901.24
#Mann= 3 , 0 , 0
       0      .1       0   540.9    .045       0   555.9      .1       0
Bank Sta=540.9,555.9
XS Rating Curve= 0 ,0
Exp/Cntr=0.3,0.1

Type RM Length L Ch R = 1 ,8741.1  ,184.5,209.8,235.7
XS GIS Cut Line= 4
     1856083.659      251199.797     1855664.307      250948.071
     1855419.649      250941.608     1855104.311      250833.729
#Sta/Elev= 30
       0 2087.44    79.8 2068.53   104.8  2063.7   139.7 2060.72   169.7 2055.47
   184.7 2050.95   219.6 2033.99   239.6 2020.65   264.5 2001.98   299.4 1979.39
   349.4 1952.33   399.3 1928.16   444.2 1905.22   489.1 1884.46   529.1  1872.5
     594 1860.53     609 1859.54   626.6 1856.77     634 1856.17   641.6 1857.69
   653.9 1862.33   683.9 1877.62   698.9 1884.28   798.5  1937.6   813.4 1944.66
   883.1 1967.76   947.7 1994.15   992.5 2009.79  1027.3 2023.24  1067.1 2035.93
#Mann= 3 , 0 , 0
       0      .1       0   626.6    .045       0   641.6      .1       0
Bank Sta=626.6,641.6
XS Rating Curve= 0 ,0
Exp/Cntr=0.3,0.1

Type RM Length L Ch R = 1 ,8531.2  ,266.4,247,227.7
XS GIS Cut Line= 4
     1856047.029      251069.691     1855694.716      250886.558
     1855628.439      250760.981     1855297.055       250642.38
#Sta/Elev= 30
       0 2094.79    34.7  2084.8    64.5 2068.78    94.3 2050.21   124.1 2036.98
   198.5 1988.43     278 1943.47   307.7 1930.35   327.6 1918.71   337.5 1911.76
   367.3 1887.11   397.1 1867.06   421.6 1855.39   431.3 1853.15   446.6  1852.3
   461.6 1852.09   490.1  1851.5   514.6 1855.11     549 1863.98   573.8    1873
   608.5 1888.72   677.9 1926.74   707.6 1944.51   732.4 1961.39   767.1 1983.01
   791.9 2002.67   801.8 2009.11   851.4 2034.65   866.2 2043.51     891 2054.36
#Mann= 3 , 0 , 0
       0      .1       0   446.6    .045       0   461.6      .1       0
Bank Sta=446.6,461.6
XS Rating Curve= 0 ,0
Exp/Cntr=0.3,0.1

Type RM Length L Ch R = 1 ,8284.2  ,196.3,197.5,198.7
XS GIS Cut Line= 4
     1856167.374       250692.96     1855914.476      250661.566
     1855670.298      250598.777     1855368.564      250455.759
#Sta/Elev= 30
       0 1998.74      35 1989.83      65 1976.77    99.9 1969.24   154.9 1951.89
   179.9 1945.76   219.9 1930.75   239.8 1920.92   264.7 1913.18   314.2  1879.4
   348.8 1852.16   353.7 1849.42     372 1845.35   373.5 1845.24     387 1846.35
     413 1850.69   447.6 1852.27   467.4 1855.05   487.2    1856   516.9 1870.08
   526.9 1875.27   546.8 1888.24   571.8 1901.71   591.7 1914.38   616.6 1928.02
   686.4  1974.2   746.2 2008.31   776.1  2028.6     801 2047.74   840.9 2069.69
#Mann= 3 , 0 , 0
       0      .1       0     372    .045       0     387      .1       0
Bank Sta=372,387
XS Rating Curve= 0 ,0
Exp/Cntr=0.3,0.1

Type RM Length L Ch R = 1 ,8086.7  ,160.6,155.5,150.5
XS GIS Cut Line= 4
     1856270.277      250560.406     1855940.637      250478.433
      1855755.76      250420.876     1855440.074      250361.576
#Sta/Elev= 30
       0 2056.29      30 2041.01    64.9 2025.05   129.9 1999.21   164.8 1977.37
   194.8 1960.69   229.8  1942.6   334.7 1890.73   354.6 1882.25   364.5 1878.97
   419.1 1867.09   458.8 1845.84   468.8  1841.7   473.7    1841   477.7 1841.05
   492.7 1842.95   513.4 1847.63     558 1865.36     563 1867.66   602.5 1892.61
   627.2 1903.98   632.1 1905.15   676.6 1934.32   711.2 1956.06   745.8 1976.63
   765.6 1990.92   800.2  2021.8     810 2029.74   839.7 2050.76   854.5 2059.72
#Mann= 3 , 0 , 0
       0      .1       0   477.7    .045       0   492.7      .1       0
Bank Sta=477.7,492.7
XS Rating Curve= 0 ,0
Exp/Cntr=0.3,0.1

Type RM Length L Ch R = 1 ,7931.1  ,127,132.2,137.3
XS GIS Cut Line= 4
      1856305.16      250387.738     1855996.449      250297.044
     1855795.875      250281.346     1855518.559       250215.07
#Sta/Elev= 30
       0 2062.29    39.6 2035.81   133.6    1980   163.4 1967.38   183.2 1957.17
   217.8 1935.61   262.4 1905.64   277.2 1897.59     302 1887.65   346.3 1872.46
   356.1 1867.49   375.7 1855.54   385.6 1851.43   400.3 1847.91   424.8 1843.73
     476 1842.24     491 1840.45   498.4 1839.72   503.3 1840.86   537.7 1854.77
     577 1875.77   631.1  1913.8   670.4 1933.16   714.7 1958.38   734.3 1970.97
   768.7 1994.61   778.6  2000.6   783.5 2002.81   788.4 2003.94   808.1 2006.65
#Mann= 3 , 0 , 0
       0      .1       0     476    .045       0     491      .1       0
Bank Sta=476,491
XS Rating Curve= 0 ,0
Exp/Cntr=0.3,0.1

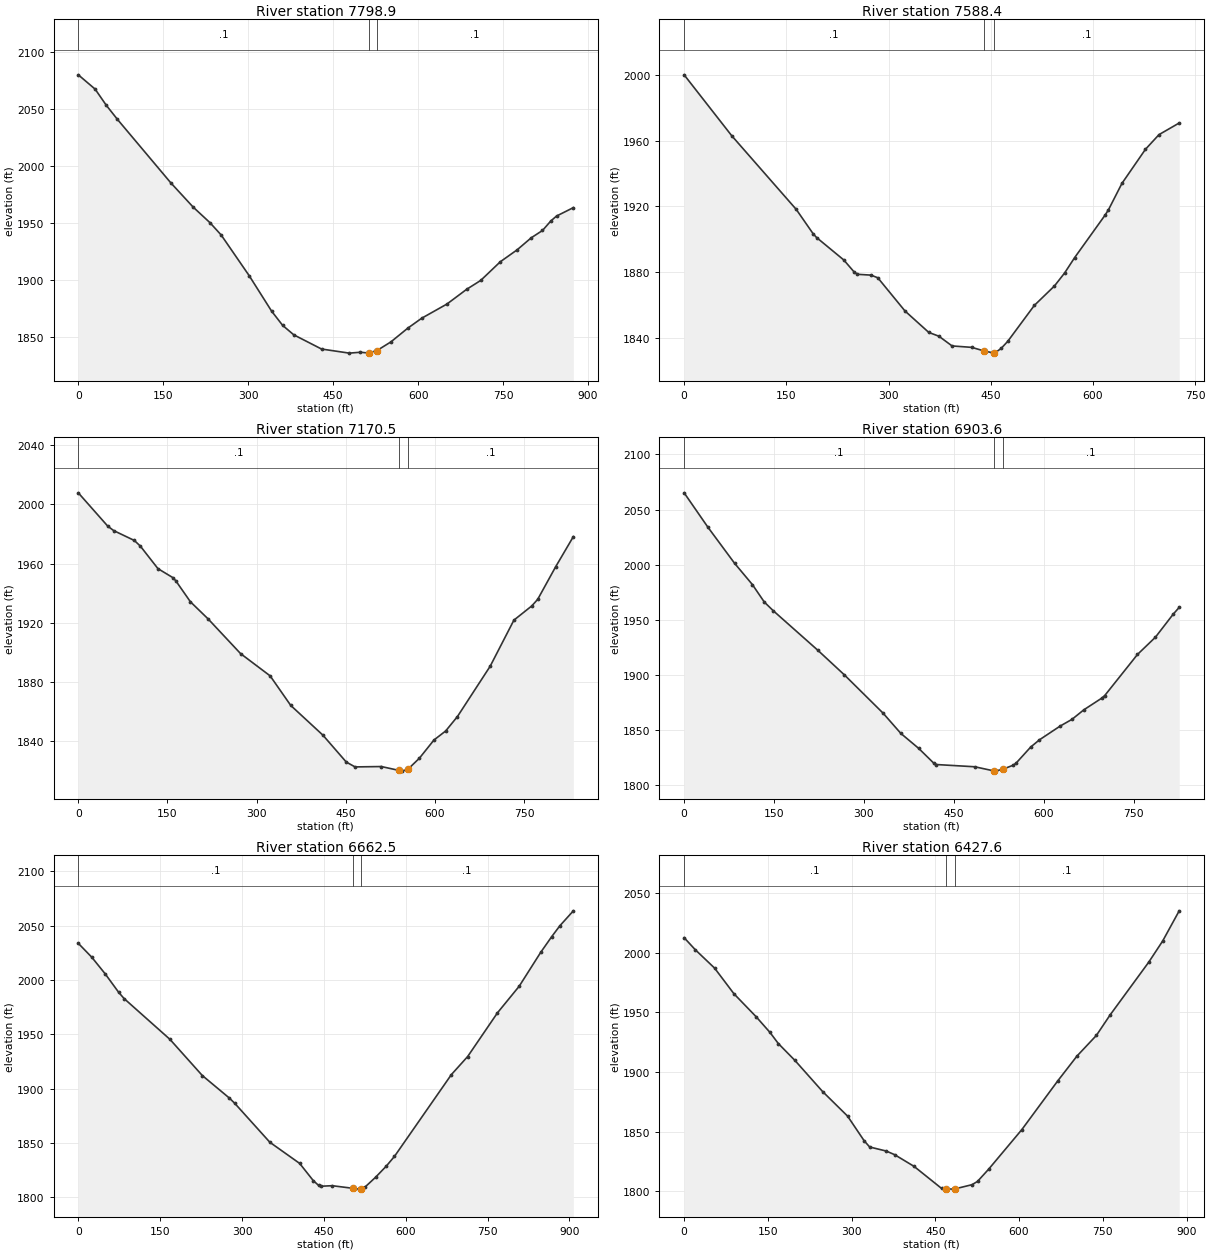
Type RM Length L Ch R = 1 ,7798.9  ,211.1,210.5,210
XS GIS Cut Line= 4
     1856350.482      250383.856     1856052.261      250217.866
     1855832.672      250148.504     1855530.768      250128.916
#Sta/Elev= 30
       0 2079.63    29.7  2067.1    49.5 2052.87    69.2  2040.5   163.2 1984.98
   202.8 1963.63   232.5 1949.96   252.3 1939.14   301.7  1903.5   341.3  1872.4
   360.9 1859.84   380.5  1851.6   429.5 1839.15   478.5 1835.56   498.1 1836.34
   512.4 1835.64   527.4 1837.84     552 1845.43   581.5 1857.36   606.3 1866.16
   650.9 1878.61   685.7 1891.53   710.5 1899.31   745.2 1915.72   774.9 1926.18
   799.7  1936.7   819.6 1943.13   834.4  1951.5   844.4 1955.78   874.1 1963.16
#Mann= 3 , 0 , 0
       0      .1       0   512.4    .045       0   527.4      .1       0
Bank Sta=512.4,527.4
XS Rating Curve= 0 ,0
Exp/Cntr=0.3,0.1

Type RM Length L Ch R = 1 ,7588.4  ,423.8,417.9,412
XS GIS Cut Line= 4
     1856398.478      250038.431     1856026.889      249995.604
     1855907.406       249958.69     1855682.894      249996.054
#Sta/Elev= 30
       0    2000    69.8 1962.95   164.6 1918.04   189.5 1903.15   194.5  1900.9
   234.4 1887.25   249.4 1880.02   254.4 1878.54   274.3 1878.04   284.3 1876.42
   324.2  1856.2   359.1 1843.16     374 1840.83   393.3 1834.92   422.2 1834.05
   439.9 1831.91   454.9 1830.59   455.8 1830.54   465.4 1833.44     475  1837.7
     514 1859.57   543.6 1871.44   558.5 1879.33   573.3 1888.74   617.8  1914.5
   622.8 1917.76   642.6 1933.86   677.2 1954.67     697 1963.57   726.7 1970.67
#Mann= 3 , 0 , 0
       0      .1       0   439.9    .045       0   454.9      .1       0
Bank Sta=439.9,454.9
XS Rating Curve= 0 ,0
Exp/Cntr=0.3,0.1

Type RM Length L Ch R = 1 ,7170.5  ,266.6,266.9,267.2
XS GIS Cut Line= 4
     1856584.219      249679.623     1856237.139      249594.161
     1855966.836      249589.013     1855762.737      249608.114
#Sta/Elev= 30
       0 2007.89    49.6 1985.33    59.6 1982.32    94.3 1975.65   104.3 1971.88
     134  1956.6   158.9 1950.56   163.8  1948.5   188.6 1934.18   218.4 1922.58
     273 1899.11   322.7 1884.06   357.4 1864.05   411.5 1843.94   450.8 1825.74
   465.6 1822.46   509.8 1822.71   540.1 1820.04   544.2 1819.61   555.1 1821.12
   573.7  1828.3   598.3 1840.66     618 1846.77   637.8 1856.53   692.8 1890.53
   732.8 1921.76   762.8 1931.36   772.8 1935.82   802.8 1957.71   832.8 1978.28
#Mann= 3 , 0 , 0
       0      .1       0   540.1    .045       0   555.1      .1       0
Bank Sta=540.1,555.1
XS Rating Curve= 0 ,0
Exp/Cntr=0.3,0.1

Type RM Length L Ch R = 1 ,6903.6  ,240,241.1,242.2
XS GIS Cut Line= 4
     1856590.106      249407.758     1856162.795      249351.074
     1855966.581      249344.533     1855774.728      249396.857
#Sta/Elev= 30
       0 2065.19    39.6 2034.08    84.2  2001.3     114 1981.94   133.8 1966.15
   148.6 1958.35     223  1922.5   267.6 1900.03     332 1865.42   361.7 1847.01
   391.4 1833.48   416.2 1820.28   421.1  1818.8     485 1816.78   517.3 1812.99
   519.4 1812.83   532.3 1814.66   548.8  1818.1   553.8 1819.96   578.3 1834.62
     593 1841.23   627.4 1853.64   647.3 1859.79   667.2 1868.48     697 1879.02
     702  1881.4   756.6 1918.63   786.5 1934.25   816.3 1955.22   826.2  1961.3
#Mann= 3 , 0 , 0
       0      .1       0   517.3    .045       0   532.3      .1       0
Bank Sta=517.3,532.3
XS Rating Curve= 0 ,0
Exp/Cntr=0.3,0.1

Type RM Length L Ch R = 1 ,6662.5  ,246.9,234.9,222.9
XS GIS Cut Line= 4
     1856563.944      249233.345     1856293.605      249124.338
     1855966.581      249102.536     1855678.801      249089.455
#Sta/Elev= 30
       0 2033.88    24.7 2021.09    49.4 2005.71    74.1 1988.71      84 1983.02
     168 1945.49   227.3 1912.21   276.7 1891.55   286.6 1886.72   351.1 1850.79
   405.7 1831.34   430.5 1815.61   440.5 1811.04   445.4 1810.35   465.3 1810.84
   502.8 1808.46     515 1807.68   517.8 1807.76   524.9 1809.31   544.8 1818.58
   564.6 1828.92   579.5 1837.84   683.8 1913.11   713.6  1929.7   768.2 1969.91
     808 1994.37   847.7 2025.76   867.6    2040   882.5 2049.99   907.3 2063.78
#Mann= 3 , 0 , 0
       0      .1       0   502.8    .045       0   517.8      .1       0
Bank Sta=502.8,517.8
XS Rating Curve= 0 ,0
Exp/Cntr=0.3,0.1

Type RM Length L Ch R = 1 ,6427.6  ,222.1,232.9,243.8
XS GIS Cut Line= 4
     1856572.665      248919.403     1856195.498      248858.359
     1856021.085      248941.204     1855709.323      248941.204
#Sta/Elev= 30
       0 2012.69    19.8 2002.65    54.6 1987.14    89.3  1965.6     129 1946.37
   153.8 1933.21   168.7  1923.9   198.5 1909.72   248.1 1883.61   292.8 1863.02
   322.5 1842.35   332.4  1837.1   362.2  1833.7   377.1 1830.67   411.8 1820.89
   461.3 1802.33   469.4 1801.97   481.1 1801.77   484.4 1801.89   515.8  1805.5
   525.6 1808.25   545.5 1818.47   604.9 1851.64   669.2 1892.48   703.8  1913.4
   738.5 1930.68   763.2 1947.91   832.5 1992.25   857.2 2009.82   886.9  2035.2
#Mann= 3 , 0 , 0
       0      .1       0   469.4    .045       0   484.4      .1       0
Bank Sta=469.4,484.4
XS Rating Curve= 0 ,0
Exp/Cntr=0.3,0.1

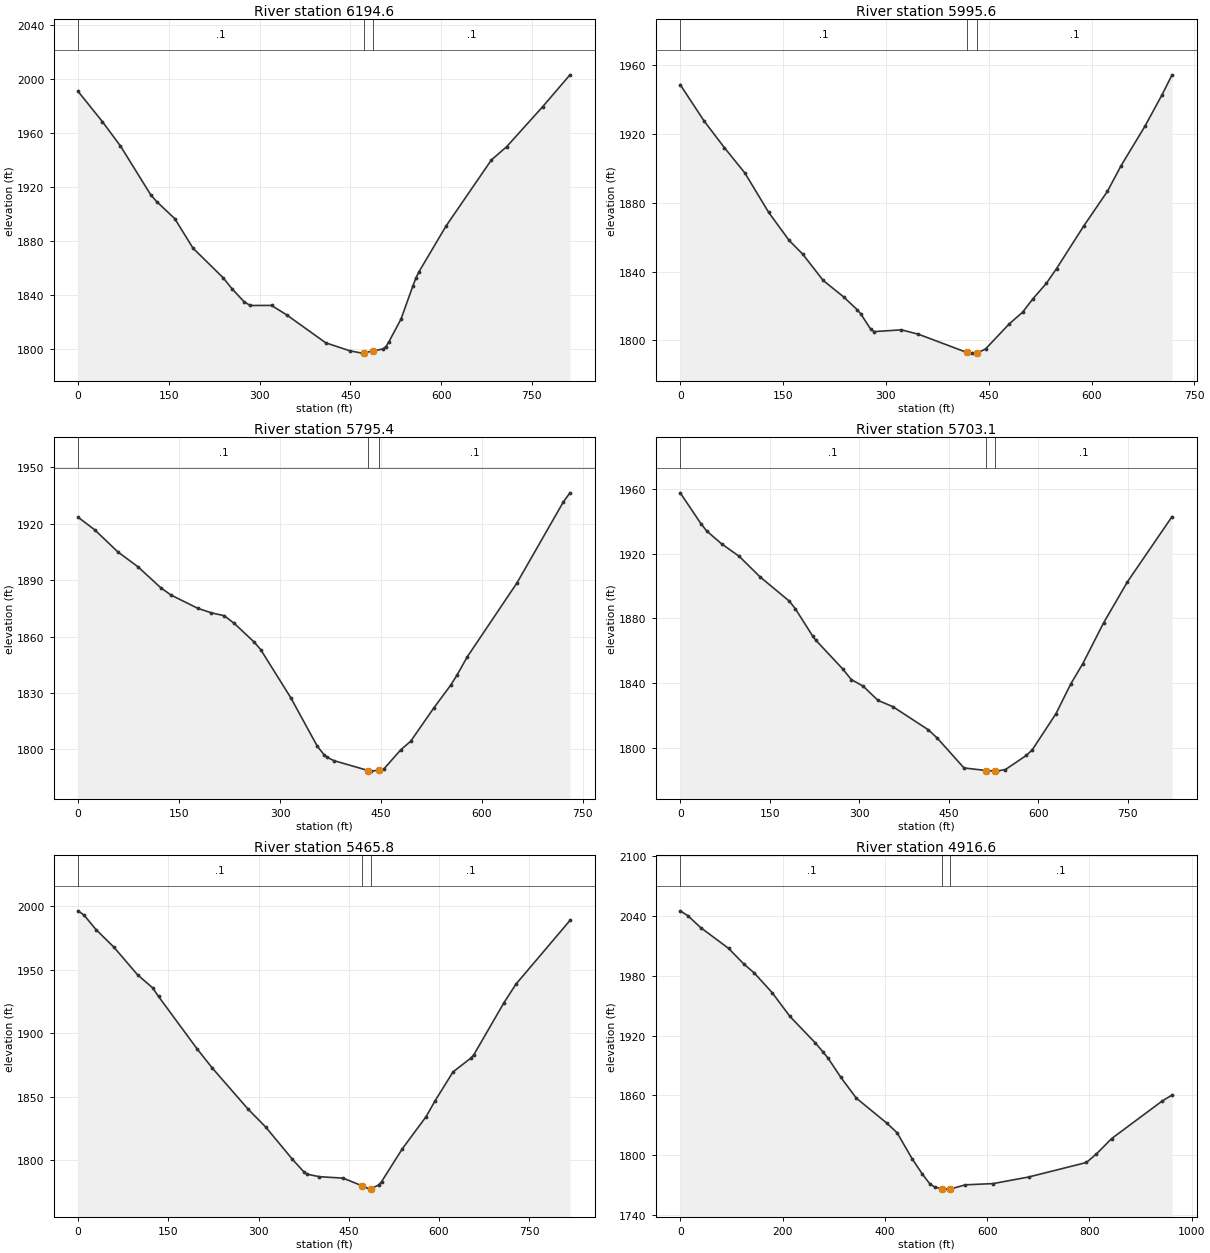
Type RM Length L Ch R = 1 ,6194.6  ,176.2,199,221.9
XS GIS Cut Line= 4
     1856524.701       248742.81     1856160.615      248679.586
      1855946.96      248673.045     1855722.404      248625.082
#Sta/Elev= 30
       0 1990.87      40 1968.52    69.9 1950.45   119.8 1914.31   129.8 1909.14
   159.8 1896.47   189.8 1874.64   239.7 1852.64   254.7 1844.28   274.6 1834.71
   284.6 1832.07   319.6 1832.13   344.6 1825.13   409.3 1804.36   449.1 1798.45
     469 1796.73   472.2 1796.93   487.2 1798.35   503.8  1799.8   508.7 1801.59
   513.7  1805.2   533.6 1821.96   553.5 1846.88   558.4 1852.63   563.4 1857.16
   608.2 1891.12   683.1 1940.11   708.1 1949.82     768 1979.68   812.9  2003.2
#Mann= 3 , 0 , 0
       0      .1       0   472.2    .045       0   487.2      .1       0
Bank Sta=472.2,487.2
XS Rating Curve= 0 ,0
Exp/Cntr=0.3,0.1

Type RM Length L Ch R = 1 ,5995.6  ,220.7,200.2,179.6
XS GIS Cut Line= 4
     1856451.184      248718.486     1856156.863      248574.596
     1856063.116      248430.705       1855845.1      248428.525
#Sta/Elev= 30
       0 1948.84    34.8 1927.73    64.5 1912.16    94.3 1897.46   129.1 1874.48
   158.8 1858.25   178.7 1850.22   208.5 1834.95   238.3 1825.37   258.1 1817.92
   263.1 1815.63     278 1806.46   282.9 1805.16   322.6 1806.19   347.2 1803.67
   418.1 1793.03   425.8 1792.64   433.1 1792.72   445.4 1795.08   479.7 1809.57
   499.4 1816.46   514.2 1824.14     534 1833.24   548.9 1841.83   588.5 1866.58
   623.2 1886.85     643 1901.69   677.7 1924.59   702.5 1942.75   717.4 1954.57
#Mann= 3 , 0 , 0
       0      .1       0   418.1    .045       0   433.1      .1       0
Bank Sta=418.1,433.1
XS Rating Curve= 0 ,0
Exp/Cntr=0.3,0.1

Type RM Length L Ch R = 1 ,5795.4  ,96.6,92.3,88
XS GIS Cut Line= 4
     1856601.523      248393.706     1856318.975      248323.828
     1856083.181      248293.752      1855884.52      248256.989
#Sta/Elev= 30
       0 1923.37    24.7 1916.67    59.2 1904.91    88.8 1897.08   123.3 1885.75
   138.1 1882.02   177.6 1875.02   197.3 1872.66   217.1 1871.05   231.9 1866.99
   261.5 1857.08   271.3 1853.02   315.8 1827.57   355.4 1801.69   365.3 1797.24
   370.3 1795.74   380.2 1794.04   431.4 1788.74   434.7 1788.47   446.4 1788.94
   454.5 1789.72   479.2 1799.73   494.1 1804.35   528.8 1822.21   553.4 1834.07
   563.3 1839.71     578 1849.11     652 1888.46   720.9 1931.48   730.8 1936.35
#Mann= 3 , 0 , 0
       0      .1       0   431.4    .045       0   446.4      .1       0
Bank Sta=431.4,446.4
XS Rating Curve= 0 ,0
Exp/Cntr=0.3,0.1

Type RM Length L Ch R = 1 ,5703.1  ,240.5,237.2,233.9
XS GIS Cut Line= 4
     1856714.375      248149.808     1856409.153      248211.649
     1856140.994      248219.573     1855896.816      248226.113
#Sta/Elev= 30
       0 1957.55    34.6 1938.57    44.5 1933.95    69.2 1926.11    98.9 1918.33
   133.5 1905.77   182.9 1890.67   192.8 1886.04   222.4 1868.88   227.4 1866.49
   271.9 1848.99   286.7 1842.28   306.5 1838.22   331.3 1829.45   356.1 1825.61
   415.8 1811.27   430.7 1806.15   475.4 1787.75   512.6 1786.16   527.6 1785.86
     530 1785.79   544.9 1786.78   579.7 1795.45   589.7 1798.88   629.6 1821.32
   654.5 1839.76   674.4 1852.09   709.3 1877.32   749.2 1902.61     824 1942.87
#Mann= 3 , 0 , 0
       0      .1       0   512.6    .045       0   527.6      .1       0
Bank Sta=512.6,527.6
XS Rating Curve= 0 ,0
Exp/Cntr=0.3,0.1

Type RM Length L Ch R = 1 ,5465.8  ,549,549.2,549.5
XS GIS Cut Line= 4
     1856673.217      248036.046     1856372.356        247953.2
     1856082.395      248014.244     1855884.001      248081.829
#Sta/Elev= 30
       0 1996.37     9.9 1992.96    29.7 1981.63    59.4 1967.83    99.1 1945.89
   123.8 1935.83   133.7 1928.98   198.1 1887.61   222.9 1872.81   282.3 1840.51
   312.1 1826.17   356.5 1800.79   376.3 1790.51   381.2 1789.12     401 1787.18
   440.5 1786.03   472.3 1780.01   484.9 1777.38   487.3 1777.69   499.7 1780.66
   504.7 1783.31   539.2 1809.16   578.7 1834.41   593.6 1846.85   623.4 1869.56
   653.3 1880.56   658.3 1883.29   708.2 1924.08   728.1 1938.65     818 1988.82
#Mann= 3 , 0 , 0
       0      .1       0   472.3    .045       0   487.3      .1       0
Bank Sta=472.3,487.3
XS Rating Curve= 0 ,0
Exp/Cntr=0.3,0.1

Type RM Length L Ch R = 1 ,4916.6  ,359.9,369.6,379.3
XS GIS Cut Line= 4
     1856614.088      247423.816     1856180.236      247434.717
     1855962.221       247478.32     1855794.349      247733.398
#Sta/Elev= 30
       0 2045.43      15  2040.5    39.9 2028.65    94.8 2007.61   124.7 1991.86
   144.7 1983.07   179.6 1963.37   214.5  1939.4   264.4 1912.64   279.4 1903.62
   289.3 1897.31   314.3 1878.04   344.2 1857.38   404.1 1832.14     424  1822.6
   453.8 1796.14   473.5 1781.04   488.3 1771.06   498.2  1767.9   512.5  1766.4
   522.9 1765.93   527.5 1765.99   557.5 1770.24   611.8  1771.5     681 1778.07
   794.2 1792.68   813.9 1801.32   843.5 1816.67     942 1854.29   961.7 1860.45
#Mann= 3 , 0 , 0
       0      .1       0   512.5    .045       0   527.5      .1       0
Bank Sta=512.5,527.5
XS Rating Curve= 0 ,0
Exp/Cntr=0.3,0.1

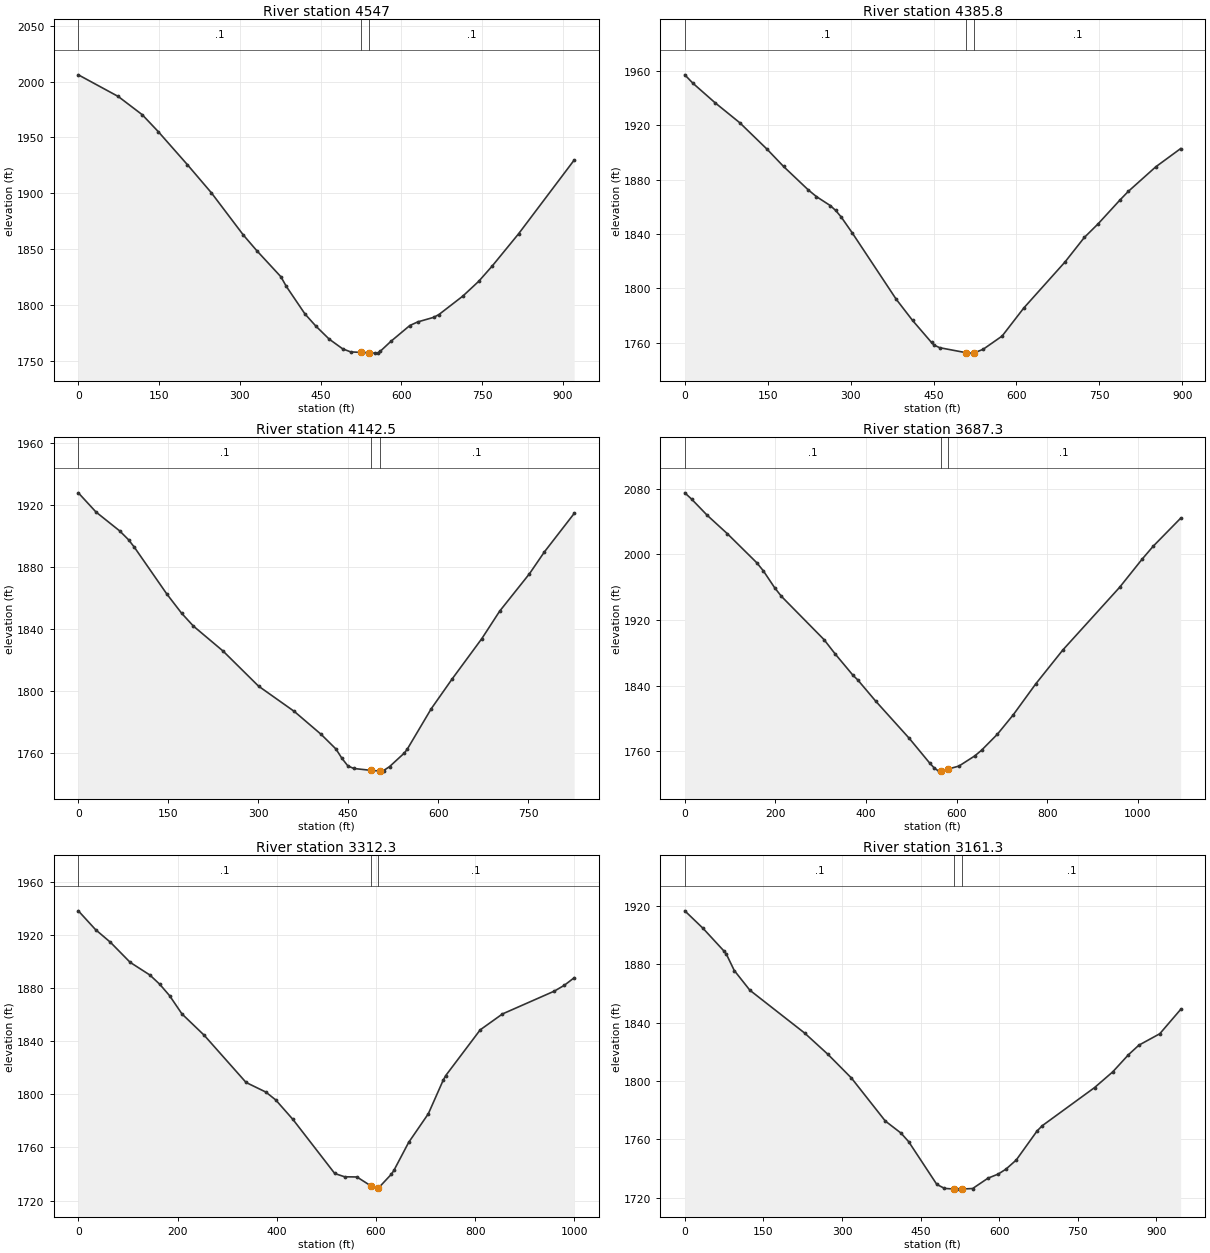
Type RM Length L Ch R = 1 ,4547    ,166.6,161.2,157.9
XS GIS Cut Line= 4
     1856596.646      247197.422     1856271.803      247132.018
     1855994.923      247066.613     1855694.062      247118.937
#Sta/Elev= 30
       0 2006.05    74.2 1986.66   118.7 1970.37   148.4 1955.28   202.8 1925.55
   247.3 1900.42   306.6 1862.67   331.4 1848.77   376.3 1825.37   386.3 1816.81
   421.2 1791.96   441.2 1781.24   466.1 1769.51   491.1 1760.84   506.1 1758.07
   524.7 1757.68   539.7 1757.31     551 1756.99     556  1757.1     561 1758.66
   580.9 1767.61   615.9 1781.71   630.6 1784.93   660.2 1789.01     670 1791.54
   714.4 1808.05   743.9 1821.27   768.6 1834.75   817.8  1863.7   921.2 1929.74
#Mann= 3 , 0 , 0
       0      .1       0   524.7    .045       0   539.7      .1       0
Bank Sta=524.7,539.7
XS Rating Curve= 0 ,0
Exp/Cntr=0.3,0.1

Type RM Length L Ch R = 1 ,4385.8  ,226.4,243.3,258.1
XS GIS Cut Line= 4
     1856593.104      247125.952     1856225.202      246940.639
     1856009.912      246921.562     1855745.568      246872.509
#Sta/Elev= 30
       0 1957.15    14.9 1950.88    54.6 1936.66    99.3 1921.94   148.9 1902.38
   178.7  1889.7   223.3 1872.49   238.2 1867.52     263 1860.98     273 1857.33
   282.9 1852.54   302.8 1840.91   382.2 1792.15   411.9 1776.48   446.3  1760.2
   451.2 1758.25   461.1 1756.36   508.4 1752.72     520 1752.37   523.4 1752.54
   539.6 1755.17     574 1764.93   613.3 1785.63   687.8 1819.46   722.7 1837.47
   747.6 1847.48   787.4 1865.15   802.3  1871.4   852.1 1889.51   896.9 1902.86
#Mann= 3 , 0 , 0
       0      .1       0   508.4    .045       0   523.4      .1       0
Bank Sta=508.4,523.4
XS Rating Curve= 0 ,0
Exp/Cntr=0.3,0.1

Type RM Length L Ch R = 1 ,4142.5  ,464.6,455.2,445.9
XS GIS Cut Line= 4
     1856642.157      247038.746     1856424.572      246886.161
     1856149.714       246649.86     1855969.034      246567.287
#Sta/Elev= 30
       0 1927.62    29.5 1915.26    68.9 1903.14    83.7 1897.44    93.5 1892.58
   147.6  1862.5   172.2 1850.17   191.9 1841.87   241.2 1825.87   300.5 1803.25
   360.1 1786.98   404.8 1772.24   429.6 1762.79   439.5 1756.84   449.5  1751.9
   459.4 1750.24   487.8 1749.05   502.8 1748.58   504.1 1748.54   509.1 1748.91
     519 1751.43   543.8 1760.22   548.8 1762.82   588.5 1788.66   623.3 1807.79
   672.9  1833.8   702.7  1851.5   752.4 1875.57   777.2 1889.57   826.9 1914.33
#Mann= 3 , 0 , 0
       0      .1       0   487.8    .045       0   502.8      .1       0
Bank Sta=487.8,502.8
XS Rating Curve= 0 ,0
Exp/Cntr=0.3,0.1

Type RM Length L Ch R = 1 ,3687.3  ,373.9,374.9,375.8
XS GIS Cut Line= 3
     1856990.469      246552.686     1856486.938      246343.164
     1855960.883      246184.391
#Sta/Elev= 30
       0 2074.83    14.9 2067.24    49.6  2047.4    94.2 2024.89   158.7 1989.76
   173.5 1979.72   198.3 1959.26   213.2 1948.76   307.4 1895.96   332.2 1878.37
   371.8 1852.21   381.8  1846.9   421.4 1821.05   495.8 1775.51   540.4 1745.71
   550.4 1739.72   560.4 1735.64   565.6 1736.15   580.6 1738.05   605.3 1741.79
   640.3 1754.19   655.3 1761.11   690.2 1780.57   725.2  1804.2   775.2 1842.13
   835.1  1883.5     960 1959.56    1010 1994.07  1034.9 2010.09  1094.9 2043.86
#Mann= 3 , 0 , 0
       0      .1       0   565.6    .045       0   580.6      .1       0
Bank Sta=565.6,580.6
XS Rating Curve= 0 ,0
Exp/Cntr=0.3,0.1

Type RM Length L Ch R = 1 ,3312.3  ,141.9,151,160.4
XS GIS Cut Line= 4
     1857077.601      246258.799     1856734.898      246037.622
     1856467.541      245945.262     1856166.156      245877.208
#Sta/Elev= 30
       0 1938.09    34.8  1923.9    64.7 1914.43   104.5 1899.32   144.2  1889.8
   164.2 1882.81     184 1874.24   208.9 1860.53   253.7 1844.49   338.2 1808.93
     378 1801.72   397.9 1795.83   432.7  1781.1     517 1740.43   536.9 1737.96
   561.7 1737.82   589.2 1731.27   601.4 1728.67   604.2 1729.16   631.2 1739.91
   636.2 1742.72   665.9 1763.76   705.7  1785.4   735.6  1810.6   740.6 1814.03
   810.3 1848.54   855.2  1860.5   959.8 1877.68   979.8 1882.04   999.7  1887.7
#Mann= 3 , 0 , 0
       0      .1       0   589.2    .045       0   604.2      .1       0
Bank Sta=589.2,604.2
XS Rating Curve= 0 ,0
Exp/Cntr=0.3,0.1

Type RM Length L Ch R = 1 ,3161.3  ,469.2,448.4,427.6
XS GIS Cut Line= 4
     1857096.353      246045.257     1856700.179      245914.009
     1856542.195      245768.178     1856228.658      245756.026
#Sta/Elev= 30
       0 1916.78    34.8 1904.78    74.5 1889.29    79.5 1886.92    94.4 1875.84
   124.2 1862.31   228.6 1832.96   273.3 1818.28     318 1802.07   382.6 1772.59
   412.4 1764.36   427.1 1758.46   480.9 1729.11   495.5 1726.39   513.7 1725.92
     520 1725.88   528.7 1725.94   549.3  1726.3   578.6  1733.4   598.2 1736.24
   612.8 1739.59   632.4 1745.83   672.2 1765.78   682.2 1769.41   781.8 1795.51
   816.6 1806.33   846.5 1818.05   866.4 1824.62   906.3 1832.45   946.1 1849.12
#Mann= 3 , 0 , 0
       0      .1       0   513.7    .045       0   528.7      .1       0
Bank Sta=513.7,528.7
XS Rating Curve= 0 ,0
Exp/Cntr=0.3,0.1