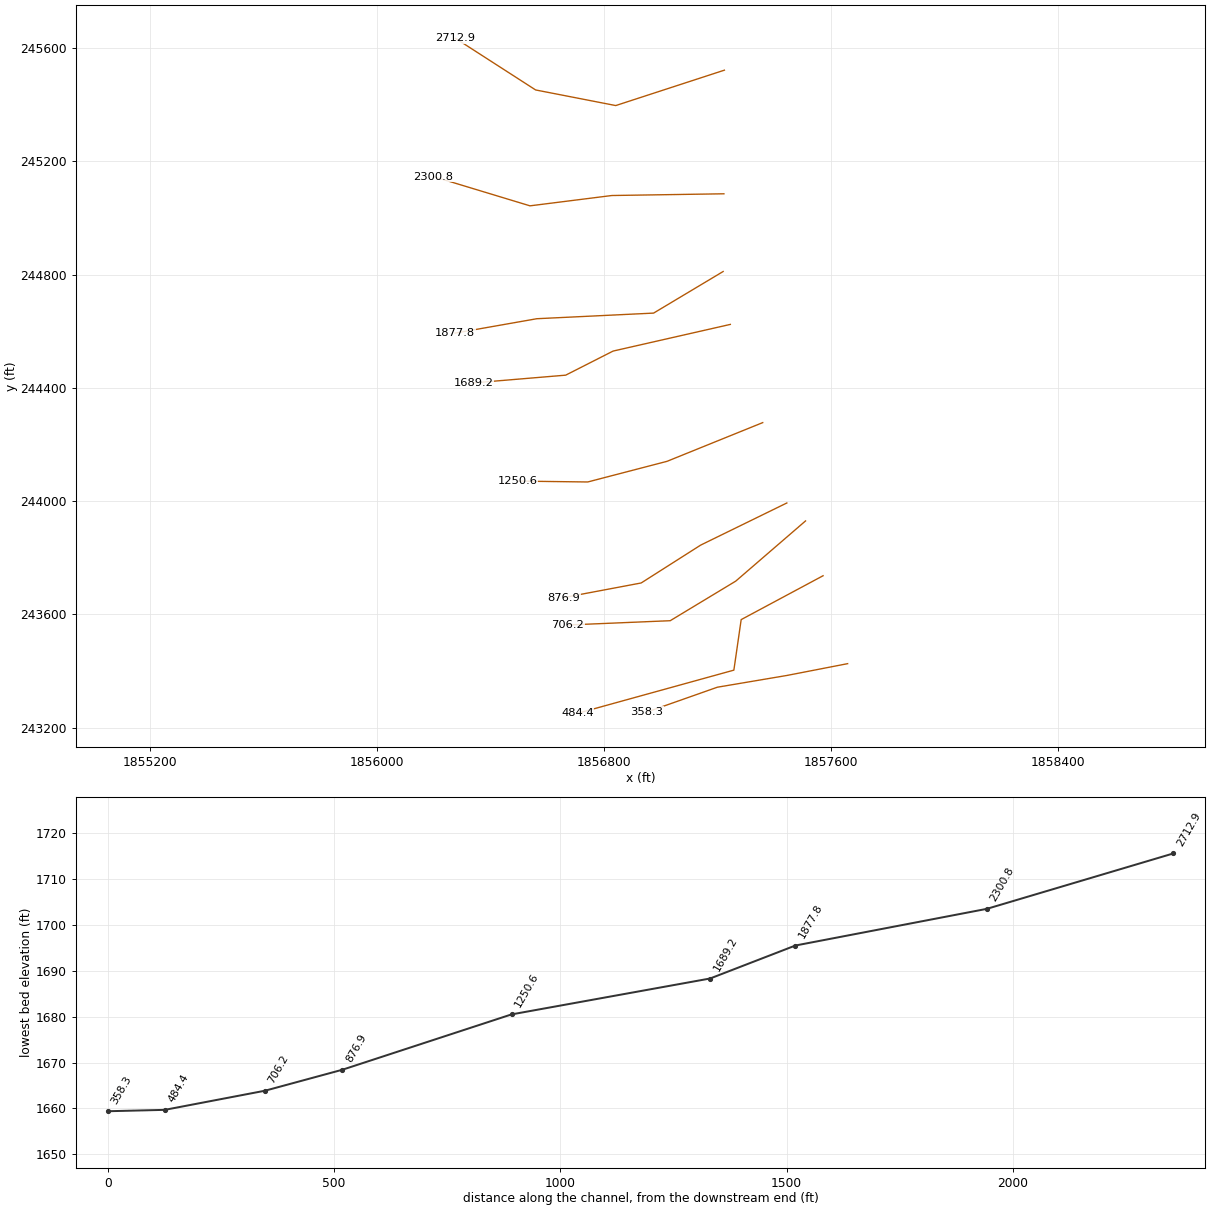
HEC-RAS study OldSlabFk.prj: OldSlabFk

--- OldSlabFk.g01 (geometry) --- (continued)

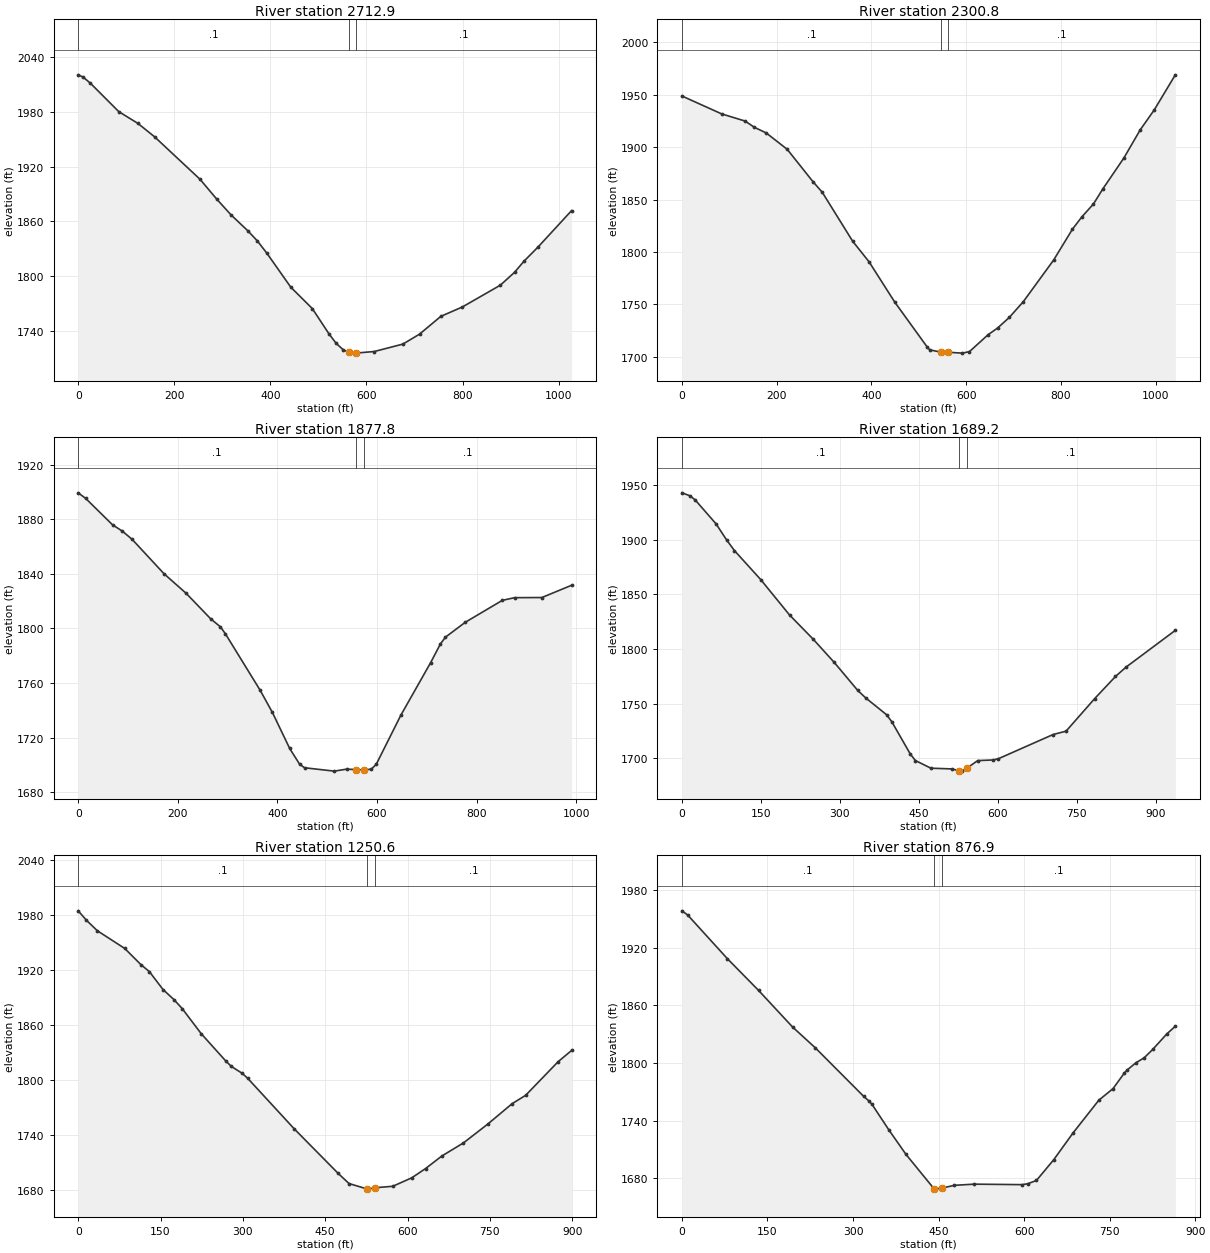
Type RM Length L Ch R = 1 ,2712.9  ,405,412.1,419.2
XS GIS Cut Line= 4
     1857225.991      245521.784     1856843.072       245396.78
     1856560.636      245451.907     1856278.089      245634.196
#Sta/Elev= 30
       0 2020.61      10 2018.19    24.9 2011.66    84.5 1980.23   124.3 1967.35
   159.1 1952.59   253.6 1906.06   288.4 1884.28   318.3 1866.95   353.1  1849.6
     373 1838.44   392.9 1824.86   442.5 1787.76   487.2 1764.38   521.9 1736.64
   536.8  1726.3   551.6 1719.12     563  1716.5   576.5  1715.5     578 1715.54
   616.2 1717.28   675.7  1725.4   710.4 1736.31   754.8 1755.84   799.4 1766.07
   878.5 1789.96   908.1 1804.07   927.9 1816.34   957.6 1832.14  1026.8 1871.74
#Mann= 3 , 0 , 0
       0      .1       0     563    .045       0     578      .1       0
Bank Sta=563,578
XS Rating Curve= 0 ,0
Exp/Cntr=0.3,0.1

Type RM Length L Ch R = 1 ,2300.8  ,435.3,423,421.8
XS GIS Cut Line= 4
     1857224.343      245085.163     1856829.384      245079.086
      1856540.76      245042.629     1856200.488      245145.926
#Sta/Elev= 30
       0 1948.74    83.9 1931.66   133.3 1924.84   153.1 1918.82   177.8 1913.53
   222.2 1897.88   276.5 1867.05   296.2 1856.88   360.4 1810.19     395 1790.55
   449.2 1752.13   518.3  1708.9   523.2 1706.53   546.2 1704.46   561.2 1704.26
   592.2 1703.44     607 1704.91   646.5 1721.11   666.2 1727.32   690.9 1737.45
   720.5 1752.46   784.7  1792.3   824.2 1821.59     844 1833.32   868.7 1845.75
   888.4 1860.06   932.9 1889.61   967.4 1916.45   997.1 1935.54  1041.5 1968.95
#Mann= 3 , 0 , 0
       0      .1       0   546.2    .045       0   561.2      .1       0
Bank Sta=546.2,561.2
XS Rating Curve= 0 ,0
Exp/Cntr=0.3,0.1

Type RM Length L Ch R = 1 ,1877.8  ,179.4,188.6,197.8
XS GIS Cut Line= 4
     1857221.576      244810.674      1856976.47      244663.804
     1856564.954      244643.961     1856276.441      244592.983
#Sta/Elev= 30
       0 1899.44    14.8 1895.42      69 1875.98    88.7 1871.34   108.4  1865.3
   172.4  1840.1   216.8 1825.77     266  1807.1   285.7 1801.18   295.7 1796.04
   365.2 1754.83     390 1738.44   424.7 1712.05   444.6 1700.53   454.5 1697.93
   514.1 1695.46   538.9  1696.9   557.9  1696.6   572.9 1696.32   588.5 1696.88
   598.5 1700.48   648.1  1736.6   707.7 1774.97   727.5  1788.8   737.5 1793.66
   777.2 1804.54   851.7 1820.64   876.5 1822.59   931.1  1822.7   990.7 1831.68
#Mann= 3 , 0 , 0
       0      .1       0   557.9    .045       0   572.9      .1       0
Bank Sta=557.9,572.9
XS Rating Curve= 0 ,0
Exp/Cntr=0.3,0.1

Type RM Length L Ch R = 1 ,1689.2  ,444.7,438.6,432.4
XS GIS Cut Line= 4
     1857246.918      244623.877      1856833.73      244529.695
     1856666.632      244444.626      1856341.55      244417.283
#Sta/Elev= 30
       0 1942.81      15 1940.14    24.9 1936.43    64.8 1914.43    84.8 1899.75
    99.7 1890.01   149.6  1863.5   204.4  1831.1   249.3 1808.98   289.2  1787.8
     334 1762.11     349  1755.3   388.9 1739.84   398.9 1733.33   433.6 1704.17
   443.5 1697.97   473.1 1690.96   512.6 1690.31     526 1688.75   532.3 1688.28
     541 1690.85     562 1697.91   591.6 1698.49   601.4 1699.65   705.2 1721.75
   729.9 1724.84   784.3 1754.63   823.8 1774.84   843.6 1783.31   937.5 1817.02
#Mann= 3 , 0 , 0
       0      .1       0     526    .045       0     541      .1       0
Bank Sta=526,541
XS Rating Curve= 0 ,0
Exp/Cntr=0.3,0.1

Type RM Length L Ch R = 1 ,1250.6  ,366.6,373.7,380.8
XS GIS Cut Line= 4
      1857361.06      244277.015     1857023.826      244140.299
     1856744.316      244067.383     1856498.226      244070.421
#Sta/Elev= 30
       0 1984.23      15 1973.94    34.9 1962.47    84.7  1943.2   114.6 1925.32
   129.6 1917.92   154.5 1898.36   174.5 1887.29   189.4 1877.58   224.3    1850
   269.2 1820.12   279.2 1814.33   299.1 1806.77   309.1 1801.25   393.8 1746.13
   473.5 1697.75   493.4 1686.56   525.9 1680.73   528.2 1680.47   540.9    1682
   573.1 1683.56   607.9 1692.86   632.8 1702.88   662.6 1716.65     702 1730.95
   746.3  1751.5   790.6 1773.75   815.2 1782.84   874.3  1819.5   898.9 1831.81
#Mann= 3 , 0 , 0
       0      .1       0   525.9    .045       0   540.9      .1       0
Bank Sta=525.9,540.9
XS Rating Curve= 0 ,0
Exp/Cntr=0.3,0.1

Type RM Length L Ch R = 1 ,876.9   ,171.3,170.7,170.2
XS GIS Cut Line= 4
     1857446.128      243993.253     1857142.313      243844.384
     1856932.681      243710.705     1856659.248      243659.057
#Sta/Elev= 30
       0 1958.72      10 1954.38    79.6 1908.84   134.3 1875.74     194 1837.53
   233.8 1815.86   318.4 1765.37   328.4  1760.1   333.4 1756.76   363.2  1729.9
     393 1704.57   441.8 1668.99   442.8 1668.43   456.8 1669.62   477.6 1672.39
   512.4 1673.62   596.9  1673.1   606.8 1674.12   621.7  1677.5   651.6 1698.82
   686.3  1727.4   731.1 1761.21   755.9 1773.23   775.8 1789.49   780.8 1792.71
   795.7 1800.05   810.6 1805.44   825.5 1814.09   850.3 1830.33   865.2 1838.34
#Mann= 3 , 0 , 0
       0      .1       0   441.8    .045       0   456.8      .1       0
Bank Sta=441.8,456.8
XS Rating Curve= 0 ,0
Exp/Cntr=0.3,0.1

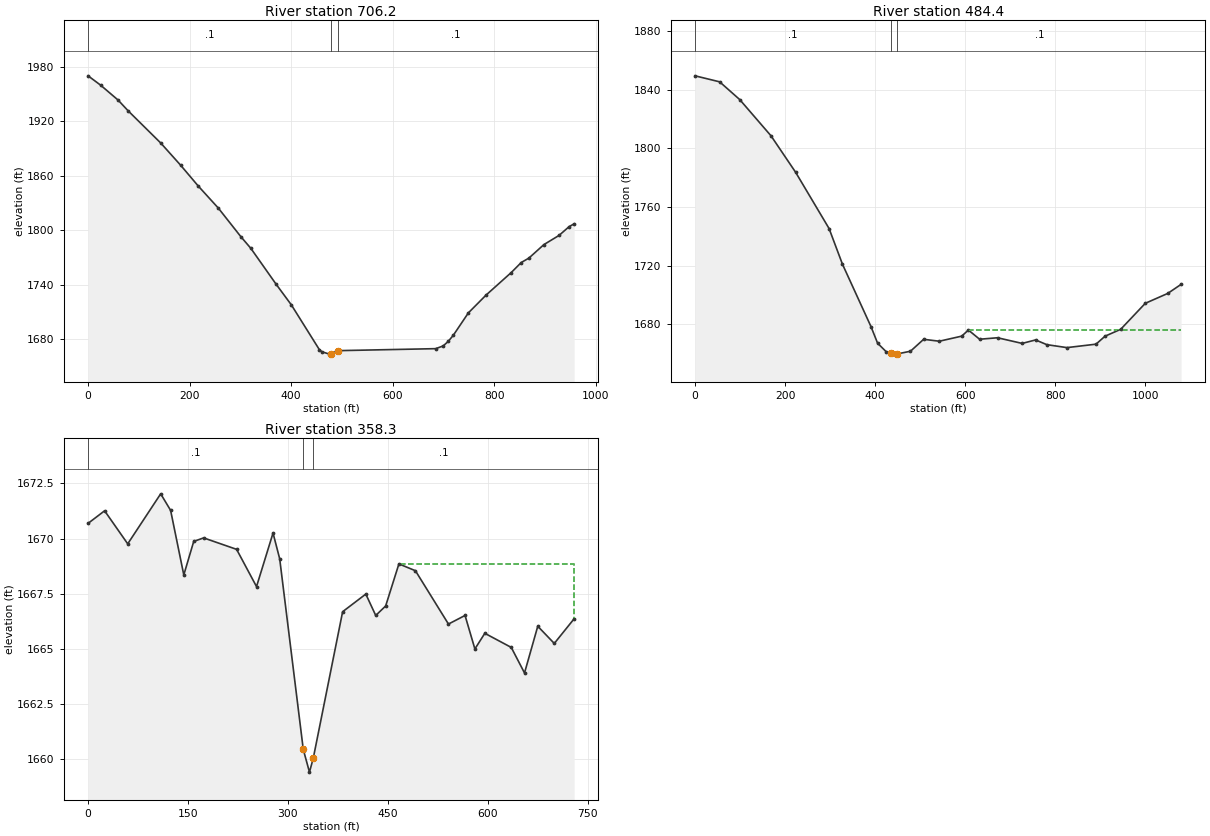
Type RM Length L Ch R = 1 ,706.2   ,199.9,221.8,243.6
XS GIS Cut Line= 4
     1857512.007      243929.835     1857265.917      243717.165
     1857035.018       243577.41     1856673.478       243562.22
#Sta/Elev= 30
       0 1969.78    24.6 1959.55    59.1 1943.12    78.8 1931.34   142.9 1896.01
   182.3 1871.47   216.8  1848.7   256.3 1824.47   300.6 1793.11   320.3 1780.25
   370.2 1740.73   400.2 1718.02   455.2 1668.95   460.2 1666.49   475.2 1663.87
   477.4 1664.35   492.4 1667.68   684.4 1669.88   699.2 1672.88   709.2 1677.94
   719.1 1684.59   748.8 1709.23   783.5 1728.72   833.1 1753.51   852.9 1764.58
   867.8 1769.38   897.5 1784.27   927.3 1794.37   947.1 1803.98     957  1807.1
#Mann= 3 , 0 , 0
       0      .1       0   477.4    .045       0   492.4      .1       0
Bank Sta=477.4,492.4
XS Rating Curve= 0 ,0
Exp/Cntr=0.3,0.1

Type RM Length L Ch R = 1 ,484.4   ,156.4,126.1,95.9
XS GIS Cut Line= 4
      1857573.73      243736.225     1857285.106      243581.279
     1857259.359      243402.818     1856707.858      243250.121
#Sta/Elev= 30
       0  1849.4    54.6 1845.31    99.3 1833.19   168.8 1808.48   223.4 1783.68
   297.8  1745.3   327.6 1720.94   390.9 1678.48   405.6 1667.14     425 1661.26
   434.6 1660.36   444.5  1659.7   449.6 1659.85   478.7 1661.69   507.9  1669.8
   542.7  1668.5   592.5 1671.96   607.4 1676.11   632.3 1669.85   672.1 1670.86
   726.8 1667.01   756.7 1669.37   781.6 1666.16   826.4 1664.14     891 1666.49
     911 1671.92   945.8 1676.61  1000.5 1694.34  1050.3 1701.06  1080.1 1707.26
#Mann= 3 , 0 , 0
       0      .1       0   434.6    .045       0   449.6      .1       0
#XS Ineff= 2 , 0
                          609.03         1675.86
Permanent Ineff=
       F       F
Bank Sta=434.6,449.6
XS Rating Curve= 0 ,0
Exp/Cntr=0.3,0.1

Type RM Length L Ch R = 1 ,358.3   ,341.5,358.3,375
XS GIS Cut Line= 4
     1857660.361      243425.732     1857446.315      243384.041
      1857201.18      243342.517     1856953.139      243254.916
#Sta/Elev= 30
       0 1670.69    24.8 1671.26    59.5 1669.76     109 1672.03   123.9 1671.28
   143.7 1668.35   158.6 1669.87   173.5 1670.03     223 1669.51   252.9 1667.82
   277.7 1670.25   287.7 1669.08   323.1 1660.43   332.4  1659.4   338.1 1660.03
   382.2 1666.68     417 1667.48   431.9 1666.51   446.8 1666.94   466.7 1668.85
   491.5 1668.54   541.1 1666.12     566 1666.51   580.8 1664.99   595.7  1665.7
   635.4 1665.06   655.3  1663.9   675.2 1666.02     700 1665.24   729.8 1666.36
#Mann= 3 , 0 , 0
       0      .1       0   323.1    .045       0   338.1      .1       0
#XS Ineff= 2 , 0
                          467.67         1668.83
Permanent Ineff=
       F       F
Bank Sta=323.1,338.1
XS Rating Curve= 0 ,0
Exp/Cntr=0.3,0.1

Chan Stop Cuts=-1
Use User Specified Reach Order=0